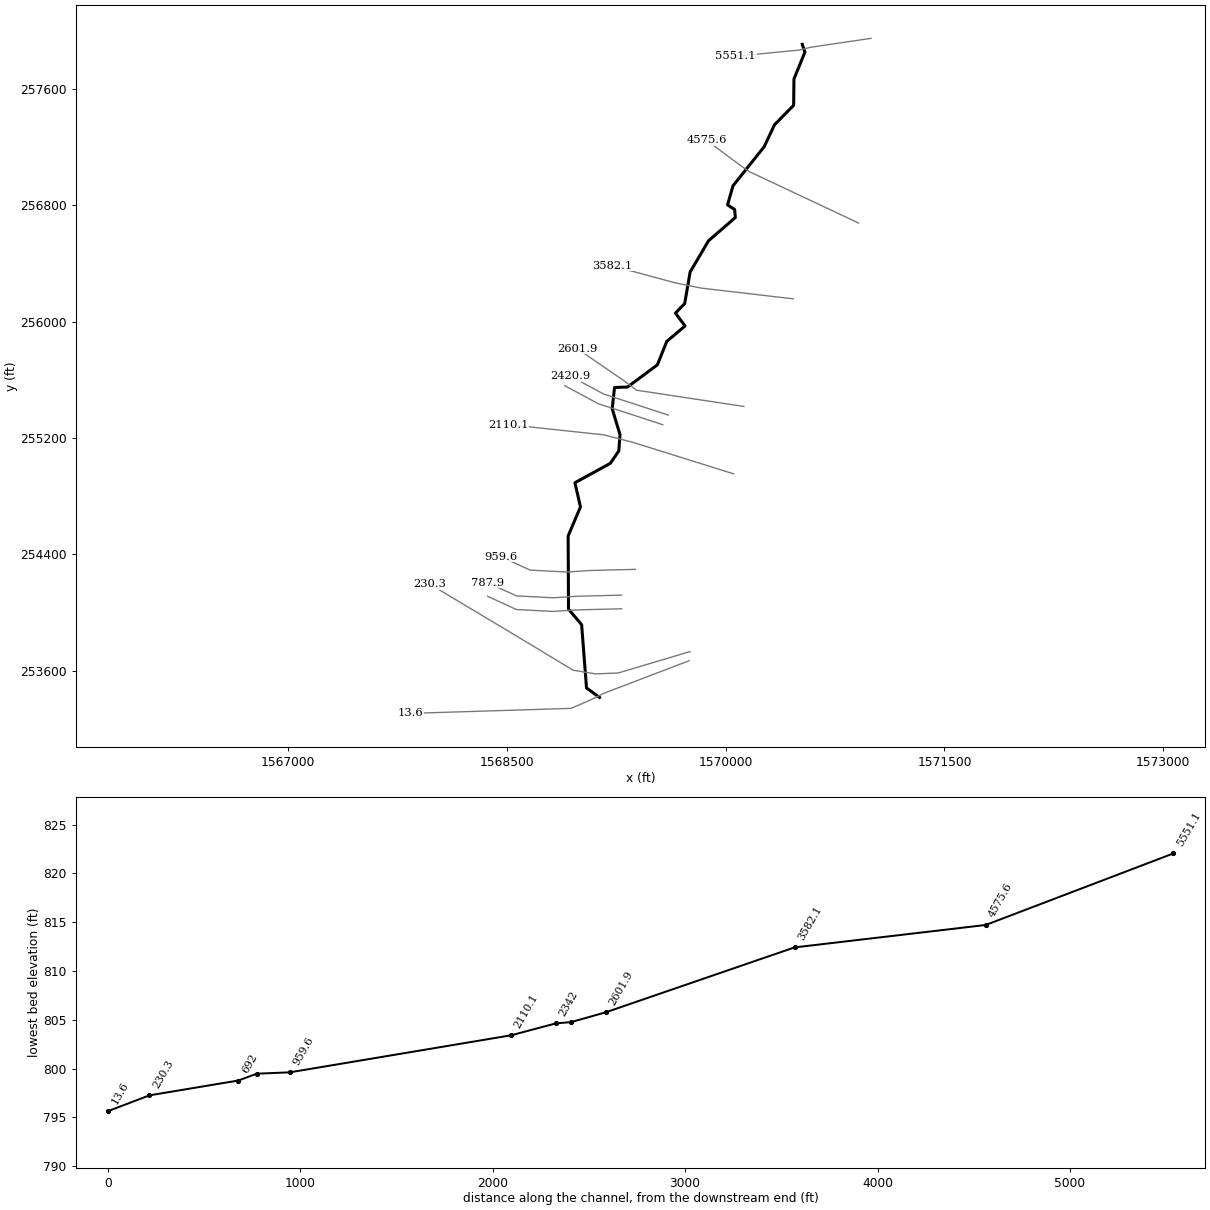
--- RFKWHTKCR.prj (project) ---

Proj Title=RFKWHTKCR
Current Plan=p01
Default Exp/Contr=0,0
English Units
Geom File=g01
Flow File=f01
Plan File=p01
BEGIN DESCRIPTION:
END DESCRIPTION:
DSS Export Rating Curves= 0
DSS Export Rating Curve Sorted= 0
DSS Export Volume Flow Curves= 0
DXF OffsetX= 0
DXF OffsetY= 0
DXF ScaleX= 0
DXF ScaleY= 0

--- RFKWHTKCR.p01 (plan) ---

Plan Title=Floodplain
Program Version=4.00
Geom File=g01
Flow File=f01
K Sum by GR=0
Std Step Tol=0.01
Critical Tol=0.01
Num of Std Step Trials=20
Max Error Tol=0.3
Flow Tol Ratio=0.001
Split Flow NTrial=30
Split Flow Tol=0.02
Split Flow Ratio=0.02
Log Output Level=0
Friction Slope Method=1
Unsteady Friction Slope Method=2
Unsteady Bridges Friction Slope Method=1
Global Log Level=0
CheckData=False
Run HTab=0
Run UNet=0
Run PostProcess=0
UNET Theta=0
UNET Theta Warmup=0
UNET ZTol=0
UNET ZSATol=0
UNET MxIter=0
UNET MaxInSteps=0
UNET DtIC=0
UNET DtMin=0
UNET MaxCRTS=0
UNET WFStab=0
UNET SFStab=0
UNET WFX=0
UNET SFX=0
UNET DSS MLevel=0
UNET DZMax Abort=0
UNET Convert EG Bridges=0
UNET Use Existing IB Tables=0
UNET Froude Limit=0
UNET Froude Power=0
Write IC File=0
Echo Input=False
Echo Output=False
Write Detailed=0

--- RFKWHTKCR.f01 (steady flow) ---

Flow Title=NFF Regression Equation
Program Version=4.10
Number of Profiles= 1
Profile Names=P100yr
River Rch & RM=RFKWHTKCR,Main            ,5551.1
972.4094
River Rch & RM=RFKWHTKCR,Main            ,2601.9
1043.138
River Rch & RM=RFKWHTKCR,Main            ,2110.1
  1284.9
River Rch & RM=RFKWHTKCR,Main            ,230.3
1299.509
Boundary for River Rch & Prof#=RFKWHTKCR,Main            , 1
Up Type= 0
Dn Type= 1
Dn Known WS=802.74
DSS Import GetInterval= 0
DSS Import GetPeak= 0
DSS Import FillOption= 0

--- RFKWHTKCR.g01 (geometry) ---

Geom Title=USGS 10m DEM
Program Version=4.10

River Reach=RFKWHTKCR       ,Main
Reach XY= 30
     1570525.125      257904.484     1570542.869      257850.223
     1570468.056      257666.243     1570465.989        257485.4
     1570334.806       257352.13     1570263.148      257199.916
     1570050.183      256932.668     1570012.779      256801.596
      1570061.45       256769.08     1570066.007      256714.173
     1569882.189      256554.739     1569755.989      256339.627
     1569718.868      256123.451       1569655.5      256057.479
     1569721.153       255969.14     1569595.903      255863.444
     1569531.649      255702.139      1569326.69      255549.758
     1569237.873      255546.449     1569221.668      255400.879
     1569275.292       255222.41     1569267.058      255110.595
     1569209.178      255025.706     1568966.206      254892.181
     1569004.126       254725.55     1568919.653      254526.825
     1568922.176      254023.763     1569012.062       253916.92
     1569045.613      253482.204     1569134.814       253417.25

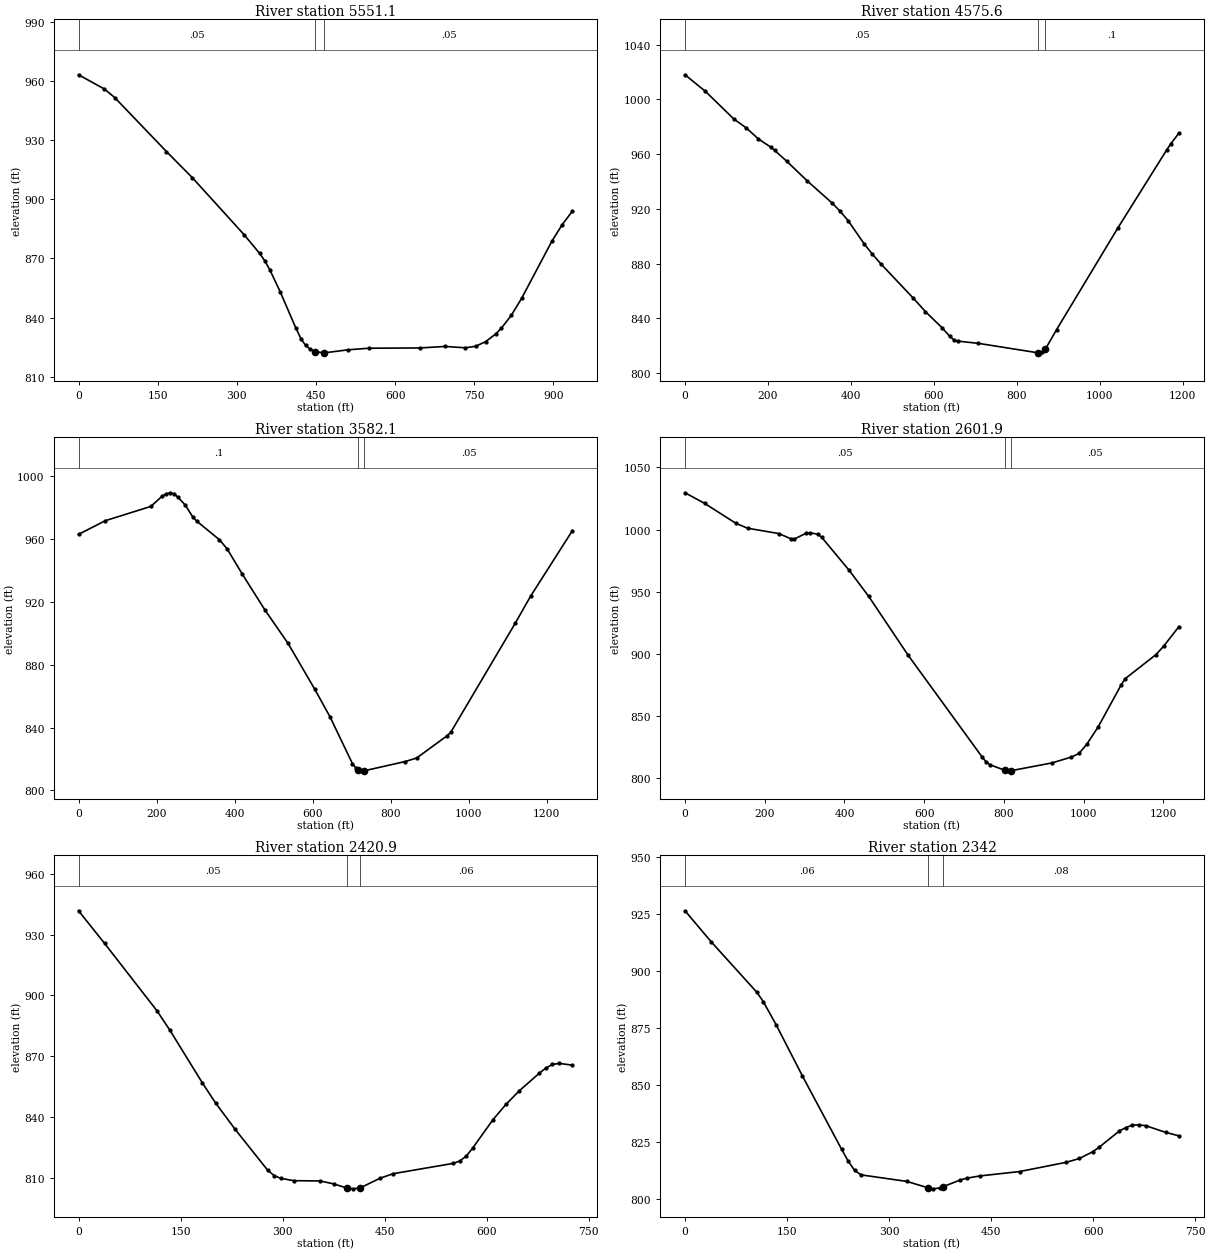
Type RM Length L Ch R = 1 ,5551.1  ,994.1,975.5,956.5
XS GIS Cut Line= 4
      1570996.44       257945.69     1570579.658      257883.769
     1570501.533      257864.672     1570069.241      257823.005
#Sta/Elev= 30
       0  963.24      49  956.02    68.6  951.66   166.6  924.27   215.6  911.02
   313.6  882.11     343  872.62   352.8  868.86   362.6   864.2   382.2  853.07
   411.6  834.81   421.4  829.31   430.3  825.83   439.2  823.86   448.2  822.63
     466  822.06   511.4  823.61     550   824.4   646.6  824.54   694.8   825.3
   733.4  824.63   752.7  825.38     772   827.8   791.3  831.79     801  834.42
   820.3  841.12   839.6  849.65   897.5   878.9   916.8  887.18   936.1  894.01
#Mann= 3 , 0 , 0
       0     .05       0   448.2    .045       0     466     .05       0
Bank Sta=448.2,466
XS Rating Curve= 0 ,0
Exp/Cntr=0.3,0.1

Type RM Length L Ch R = 1 ,4575.6  ,982.8,993.4,1002.2
XS GIS Cut Line= 4
     1570911.371      256676.593     1570164.532      257028.602
      1570114.38      257062.589     1569869.704      257244.301
#Sta/Elev= 30
       0 1017.97    49.2 1005.85     118  985.59   147.4  979.21   176.9  971.08
   206.4  965.17   216.2   962.7   245.7  954.65   294.9  940.36   353.8  924.47
   373.5   918.4   393.2  911.41   432.5   894.2   452.1  886.74   471.8  879.91
   550.4  854.72   579.9  844.82   619.2  833.24   638.9  826.67   648.7  824.09
   658.5  823.28   707.7  821.65   851.6  814.72   860.3  815.16   868.9  817.38
     896  831.66  1043.5  905.84  1161.5     963  1171.3  967.49    1191  975.28
#Mann= 3 , 0 , 0
       0     .05       0   851.6    .045       0   868.9      .1       0
Bank Sta=851.6,868.9
XS Rating Curve= 0 ,0
Exp/Cntr=0.3,0.1

Type RM Length L Ch R = 1 ,3582.1  ,964.6,980.3,949.2
XS GIS Cut Line= 4
     1570463.454       256155.76      1569833.13      256229.255
     1569653.443      256265.714     1569221.151      256382.901
#Sta/Elev= 30
       0  962.93    68.3  971.61   185.5  980.75   214.8  987.38   224.6  988.74
   234.3  989.41   244.1  988.77   253.8  986.86   273.4  981.63   292.9  973.98
   302.6  971.42   361.2  959.49   380.8  953.74   419.8  937.57   478.4  914.55
     537  893.53   605.3   864.4   644.2  846.94   702.1  816.96   711.8  813.95
   717.5  813.16   731.1  812.42   732.5  812.47   837.4  818.36   866.6  820.59
   944.5  834.73   954.3  837.08  1119.8  906.63  1158.7  923.63  1265.8  965.34
#Mann= 3 , 0 , 0
       0      .1       0   717.5    .045       0   732.5     .05       0
Bank Sta=717.5,732.5
XS Rating Curve= 0 ,0
Exp/Cntr=0.3,0.1

Type RM Length L Ch R = 1 ,2601.9  ,164.3,181,189.9
XS GIS Cut Line= 4
     1570124.912      255416.176     1569387.933      255528.156
     1569301.996       255593.26     1568984.287       255812.01
#Sta/Elev= 30
       0 1029.57      49 1021.09   127.5    1005   156.9 1001.05   235.4  996.74
   264.8  992.64   274.6  992.41   304.1  997.05   313.9  997.42   333.5  996.13
   343.3  993.59     412  967.07     461  946.11   559.1  899.11   745.4  816.92
   755.2  813.03     765  810.71   803.2  806.09     814  805.77   818.2  805.91
   920.8  812.16     969  816.84   988.3  819.75  1007.5  826.97  1036.5  841.12
  1094.3  875.04    1104  879.86  1181.1  899.23  1200.4  905.94    1239  921.81
#Mann= 3 , 0 , 0
       0     .05       0   803.2    .045       0   818.2     .05       0
Bank Sta=803.2,818.2
XS Rating Curve= 0 ,0
Exp/Cntr=0.3,0.1

Type RM Length L Ch R = 1 ,2420.9  ,79.6,78.8,79
XS GIS Cut Line= 4
     1569606.568      255356.859     1569296.672      255458.422
     1569166.463      255500.089     1568934.693      255625.089
#Sta/Elev= 30
       0   941.7    38.4  925.59   115.1  892.54   134.3  882.88   182.2  856.87
   201.4  847.08   230.2  834.09   278.2  813.89   287.8  811.25   297.3  809.93
   316.5  808.78   355.4  808.65   374.9   807.2   394.5  805.19   404.2  804.76
   414.1  805.22   443.3  809.98   462.8  812.23   550.6  817.28   560.4  818.42
   570.1  820.88   579.9  824.99   609.1  838.71   628.6   846.4   648.1  853.05
   677.4  861.67   687.1  864.27   696.9     866   706.6  866.56   726.2  865.66
#Mann= 3 , 0 , 0
       0     .05       0   394.5    .045       0   414.1     .06       0
Bank Sta=394.5,414.1
XS Rating Curve= 0 ,0
Exp/Cntr=0.3,0.1

Type RM Length L Ch R = 1 ,2342    ,226.9,232,231.8
XS GIS Cut Line= 4
     1569568.373      255290.887     1569258.477       255392.45
     1569128.269      255434.116     1568896.498      255559.116
#Sta/Elev= 30
       0  926.59    38.4  913.02   105.5  890.89   115.1  886.76   134.3  876.42
   172.6  854.16   230.2  822.01   239.8  816.86   249.4  812.71     259  810.75
   326.1  807.89   357.4  805.08   365.2  804.63   374.9  805.03  379.32805.5532
   404.2  808.45     414  809.28   433.5  810.29   492.1  812.22   560.4  816.25
   579.9  817.94   599.4  820.88   609.1  822.91   638.4  829.95   648.1   831.5
   657.9  832.56   667.6  832.68   677.4  832.34   706.6  829.41   726.2  827.88
#Mann= 3 , 0 , 0
       0     .06       0   357.4    .045       0  379.32     .08       0
Bank Sta=357.4,379.32
XS Rating Curve= 0 ,0
Exp/Cntr=0.3,0.1

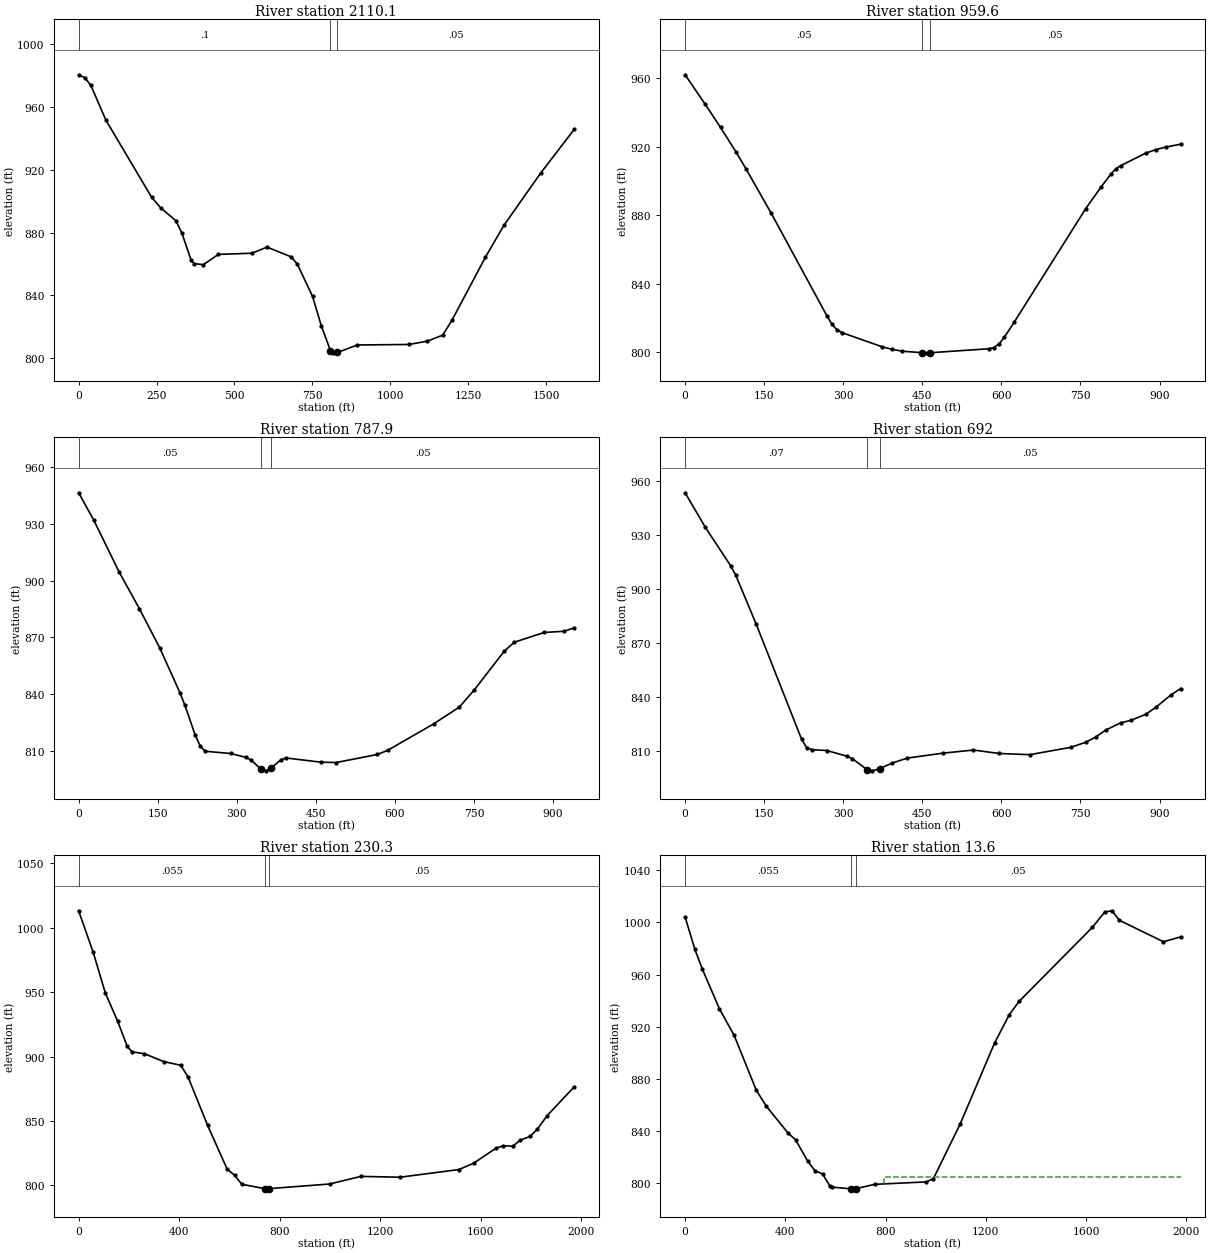
Type RM Length L Ch R = 1 ,2110.1  ,1143.2,1150.5,1149.8
XS GIS Cut Line= 4
     1570054.484      254953.214     1569356.568      255171.964
     1569161.255      255221.443     1568507.609      255291.755
#Sta/Elev= 30
       0  980.39    19.5  978.57      39  973.73    87.8  951.42     234   902.5
   263.3  895.72   312.1  887.51   331.6   879.5   360.8  862.48   370.6  860.26
   399.8  859.48   448.6  866.07   555.9  866.81   604.6   870.7   682.6  864.48
   702.1  859.77   750.6  839.39   779.4  820.25   808.2  804.83   817.8  803.41
  830.48803.6288   894.5  808.41  1060.4  808.74  1119.3  810.85  1168.4  814.68
  1197.8  824.04  1305.7  864.38  1364.6   884.5  1482.4  917.72  1590.3  945.62
#Mann= 3 , 0 , 0
       0      .1       0   808.2    .045       0  830.48     .05       0
Bank Sta=808.2,830.48
XS Rating Curve= 0 ,0
Exp/Cntr=0.3,0.1

Type RM Length L Ch R = 1 ,959.6   ,171.8,171.7,173
XS GIS Cut Line= 5
     1569380.005      254296.964     1569072.713      254289.151
     1568911.255      254278.734     1568658.651      254291.755
     1568460.734      254382.901
#Sta/Elev= 30
       0  962.13    38.4  944.78    67.2  931.38    96.1  917.26   115.3  907.28
   163.3  881.23     269  821.25   278.6  816.35   288.2     813   297.8   811.4
     374  803.12     393  801.63   412.1  800.56   449.6   799.7   459.7  799.61
   464.6  799.66   576.2     802   585.9  802.71   595.6  804.87   605.4  808.61
   624.8  817.78     760  883.93   788.4  896.26   807.4  903.97   816.9  907.09
   826.3  909.02   873.7  916.31   892.6  918.35   911.6  919.85     940  921.58
#Mann= 3 , 0 , 0
       0     .05       0   449.6    .045       0   464.6     .05       0
Bank Sta=449.6,464.6
XS Rating Curve= 0 ,0
Exp/Cntr=0.3,0.1

Type RM Length L Ch R = 1 ,787.9   ,95.7,95.8,95.6
XS GIS Cut Line= 5
     1569286.255       254119.88     1568978.963      254112.068
     1568817.505      254101.651     1568564.901      254114.672
     1568366.984      254205.818
#Sta/Elev= 30
       0  946.42    28.8  931.92    76.8  904.56   115.3  885.15   153.7  864.54
   192.1  840.79   201.7  834.03   220.9  818.56   230.5   812.6   240.2  809.81
   288.2  808.64   316.9  806.63   326.4  805.31   346.3  800.34     355  799.47
   364.5  800.83   383.5  805.26     393   806.3   459.7  804.04   488.6  803.87
   566.5  808.11   585.9  810.26   673.5   824.3   722.1  833.15   750.6  842.24
   807.4  862.73   826.3  867.43   883.2  872.61   921.1  873.23     940  875.06
#Mann= 3 , 0 , 0
       0     .05       0   346.3    .045       0   364.5     .05       0
Bank Sta=346.3,364.5
XS Rating Curve= 0 ,0
Exp/Cntr=0.3,0.1

Type RM Length L Ch R = 1 ,692     ,472.4,461.8,454.6
XS GIS Cut Line= 5
     1569286.255       254026.13     1568978.963      254018.318
     1568817.505      254007.901     1568564.901      254020.922
     1568366.984      254112.068
#Sta/Elev= 30
       0  953.45    38.4  934.23    86.4  912.86    96.1  907.58   134.5  880.65
   220.9  816.38   230.5  811.71   240.2  810.54     269  810.07   307.4  806.86
   316.9  805.63   345.5  799.37     355  798.77   369.6  800.06     393  803.12
   421.6  805.87   488.6  808.59     547  810.34   595.6  808.43     654  807.77
   731.6  811.85     760  814.66     779   817.6   797.9  821.45   826.3  825.49
   845.3  826.81   873.7  830.19   892.6  834.02   921.1  840.88     940  844.55
#Mann= 3 , 0 , 0
       0     .07       0   345.5    .045       0   369.6     .05       0
Bank Sta=345.5,369.6
XS Rating Curve= 0 ,0
Exp/Cntr=0.3,0.1

Type RM Length L Ch R = 1 ,230.3   ,195.6,216.7,230.4
XS GIS Cut Line= 6
     1569755.005      253731.859     1569263.686      253585.158
     1569107.436      253578.648     1568952.922      253604.255
     1568674.276      253773.526     1567971.151      254195.401
#Sta/Elev= 30
       0 1013.16      58  980.92   106.4   949.2   154.8  927.63   193.5   907.8
   212.8  903.64   261.2   902.2   338.6  896.07   406.3  893.17   435.4  884.13
   512.8  846.73     591  812.52   620.3  807.84   649.6  800.77   740.3   797.4
   747.4  797.25  759.29797.4297   998.4     801    1123  806.91  1278.7  806.28
    1513  812.22  1571.5  817.09  1659.4  828.67  1688.7   830.7  1727.7  830.38
    1757  835.02  1796.1  837.96  1825.3  843.62  1864.4  854.11  1971.8  876.44
#Mann= 3 , 0 , 0
       0    .055       0   740.3    .045       0  759.29     .05       0
Bank Sta=740.3,759.29
XS Rating Curve= 0 ,0
Exp/Cntr=0.3,0.1

Type RM Length L Ch R = 1 ,13.6    ,1,13.6,26.2
XS GIS Cut Line= 5
     1569748.891      253668.969     1569163.822       253445.01
     1569073.544      253399.872     1568939.997      253341.756
     1567836.602       253307.38
#Sta/Elev= 30
       0 1004.11    39.2  979.24    68.5  964.25     137  933.65   195.8  913.29
   283.9  871.33     323  859.27   411.1   838.3   440.5  833.37   489.4  816.78
   518.8  809.41   548.2  807.09   577.5  797.87   587.3  796.91   663.2  795.63
   672.4  795.62   681.5  795.75   756.5  799.08     961  800.92   990.3   803.3
  1097.7  845.48  1234.5   907.4  1293.1  929.08  1332.2  939.33  1625.3  996.25
  1674.1 1007.92  1703.4 1008.87  1732.7 1001.55  1908.6  985.11    1977  988.85
#Mann= 3 , 0 , 0
       0    .055       0   663.2    .045       0   681.5     .05       0
#XS Ineff= 2 , 0
                          792.09          804.73
Permanent Ineff=
       F       F
Bank Sta=663.2,681.5
XS Rating Curve= 0 ,0
Exp/Cntr=0.3,0.1

Chan Stop Cuts=-1
Use User Specified Reach Order=0
Composite Channel Slope=5